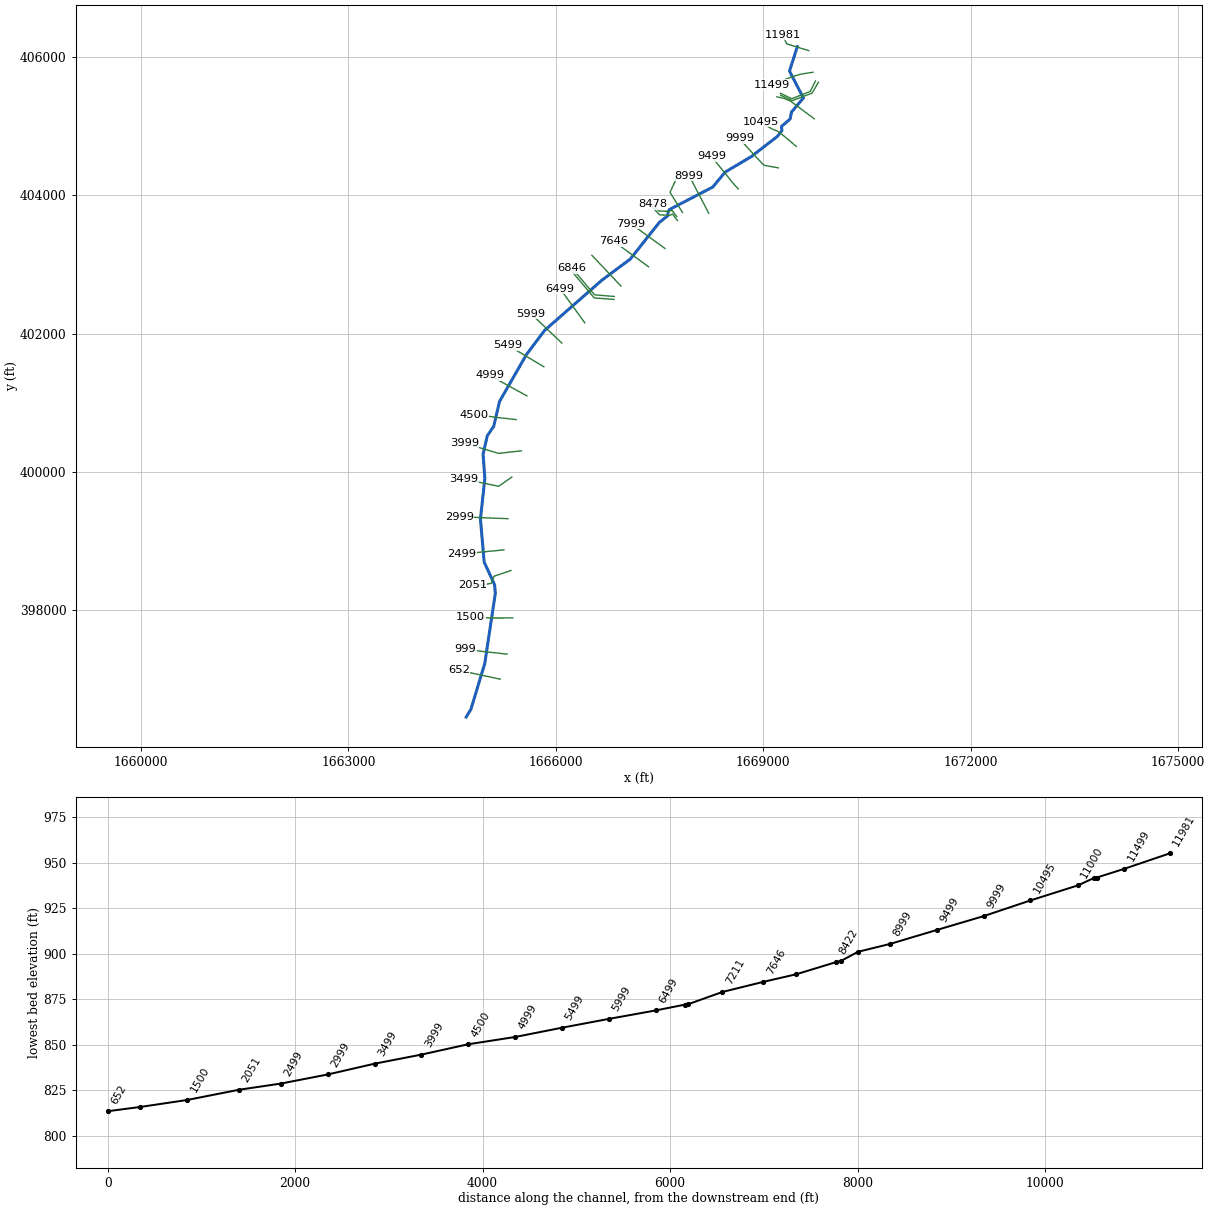
--- BIGRN.prj (project) ---

Proj Title=BIGRN
Current Plan=p01
Default Exp/Contr=0,0
English Units
Geom File=g01
Flow File=f01
Plan File=p01
BEGIN DESCRIPTION:
---------- MODELED AS PART OF WVEMD CTP PROGRAM, 2023----------
Stream Name: Big Run
Flood Zone:  AFH
Wetzel County, WV
HEC-RAS Version: RAS 6.3
Vertical Datum: NAVD88
Projection: NAD 1983 StatePlane West Virginia S FIPS 4702 (US Feet)
Terrain: 1-meter West Virginia FEMA R3 South Central (collected 2018-2020)
Land Use: 2019 NLCD
Hydrologic Method:
WV 2010 Regional Regression Equations
Additional Model Notes:
None
END DESCRIPTION:
DSS Export Rating Curves= 0
DSS Export Rating Curve Sorted= 0
DSS Export Volume Flow Curves= 0
DXF OffsetX= 0
DXF OffsetY= 0
DXF ScaleX= 0
DXF ScaleY= 0

--- BIGRN.p01 (plan) ---

Plan Title=Floodplain
Program Version=6.30
Short Identifier=Floodplain
Geom File=g01
Flow File=f01
Subcritical Flow
K Sum by GR= 0
Std Step Tol= 0.01
Critical Tol= 0.01
Num of Std Step Trials= 20
Max Error Tol= 0.3
Flow Tol Ratio= 0.001
Split Flow NTrial= 30
Split Flow Tol= 0.02
Split Flow Ratio= 0.02
Log Output Level= 0
Friction Slope Method= 1
Unsteady Friction Slope Method= 2
Unsteady Bridges Friction Slope Method= 1
Parabolic Critical Depth
Global Vel Dist= 0 , 0 , 0
Global Log Level= 0
CheckData=False
Encroach Param=-1 ,0,0, 0
Mapping Interval=1HOUR
Computation Time Step Use Courant=        0
Computation Time Step Use Time Series=    0
Computation Time Step Count To Double=0
Computation Time Step Max Doubling=0
Computation Time Step Max Halving=0
Computation Time Step Residence Courant=0
Run HTab= 0
Run UNet= 0
Run Sediment= 0
Run PostProcess= 0
Run WQNet= 0
Run RASMapper=-1
UNET Theta= 0
UNET Theta Warmup= 0
UNET ZTol= 0
UNET ZSATol= 0
UNET MxIter= 0
UNET Max Iter WO Improvement= 0
UNET MaxInSteps= 0
UNET DtIC= 0
UNET DtMin= 0
UNET MaxCRTS= 0
UNET WFStab= 0
UNET SFStab= 0
UNET WFX= 1
UNET SFX= 1
UNET Gravity=32.17405
UNET 1D Methodology=Finite Difference
UNET DSS MLevel= 1
UNET Pardiso=0
UNET DZMax Abort= 0
UNET Use Existing IB Tables= 0
UNET Froude Reduction=False
UNET Froude Limit= 0
UNET Froude Power= 0
UNET D1 Cores= 0
UNET WindReference=Eulerian
UNET WindDragFormulation=Hsu (1988)
UNET D2 Coriolis=0
UNET D2 Cores= 0
UNET D2 Theta= 1
UNET D2 Theta Warmup= 1
UNET D2 Z Tol= 0.01
UNET D2 Volume Tol= 0.01
UNET D2 Max Iterations= 20
UNET D2 Equation= 0
UNET D2 RampUpFraction=0.1
UNET D2 TimeSlices= 1
UNET D2 Turbulence Formulation=Non-Conservative (original)
UNET D2 Eddy Viscosity=0.3
UNET D2 Transverse Eddy Viscosity=0.1
UNET D2 Smagorinsky Mixing=0
UNET D2 BCVolumeCheck=0
UNET D2 Cores=0
UNET D2 SolverType=PARDISO (Direct)
UNET D2 Minimum Iterations= 3
UNET D2 Maximum Iterations= 30
UNET D2 Restart Number= 10
UNET D2 Relaxation Coeff=1.3
UNET D2 SOR Precondition Iterations= 10
UNET D2 ILUT Maximum Fill= 8
UNET D2 ILUT Tolerance=1E-08
UNET D2 Convergence Tolerance=0.00001
UNET D1D2 MaxIter= 0
UNET D1D2 ZTol=0.01
UNET D1D2 QTol=0.1
UNET D1D2 MinQTol=1
Write IC File= 0
Write IC File at Fixed DateTime=0
Write IC File at Sim End=0
Echo Input=False
Echo Parameters=False
Echo Output=False
Write Detailed= 0
HDF Write Warmup=0
HDF Write Time Slices=0
HDF Flush=0
HDF Compression= 1
HDF Chunk Size= 1
HDF Spatial Parts= 1
HDF Use Max Rows=0
HDF Fixed Rows= 1
Calibration Method= 0
Calibration Iterations= 20
Calibration Max Change=0.05
Calibration Tolerance=0.2
Calibration Maximum=1.5
Calibration Minimum=0.5
Calibration Optimization Method= 1
WQ AD Non Conservative
WQ ULTIMATE=-1
WQ Max Comp Step=1HOUR
WQ Output Interval=15MIN
WQ Output Selected Increments= 0
WQ Output face flow=0
WQ Output face velocity=0
WQ Output face area=0
WQ Output face dispersion=0
WQ Output cell volume=0
WQ Output cell surface area=0
WQ Output cell continuity=0
WQ Output cumulative cell continuity=0
WQ Output face conc=0
WQ Output face dconc_dx=0
WQ Output face courant=0
WQ Output face peclet=0
WQ Output face adv mass=0
WQ Output face disp mass=0
WQ Output cell mass=0
WQ Output cell source sink temp=0
WQ Output nsm pathways=0
WQ Output nsm derived pathways=0
WQ Create Restart=0
WQ Fixed Restart=0
WQ System Summary=0
WQ Write To DSS=0
Sorting and Armoring Iterations= 10
XS Update Threshold= 0.02
Bed Roughness Predictor= 0
Hydraulics Update Threshold= 0.02
Energy Slope Method= 1
Volume Change Method= 1
Sediment Retention Method= 0
Sediment TS Multiplier= 1
Warm Up Method= 0
XS Weighting Method= 0
Number of US Weighted Cross Sections= 1
Number of DS Weighted Cross Sections= 1
Upstream XS Weight=0
Main XS Weight=1
Downstream XS Weight=0
Number of DS XS's Weighted with US Boundary= 1
Upstream Boundary Weight= 1
Weight of XSs Associated with US Boundary= 0
Number of US XS's Weighted with DS Boundary= 1
Downstream Boundary Weight= 0.5
Weight of XSs Associated with DS Boundary= 0.5
Percentile Method= 0
Sediment Output Level= 3
Mass or Volume Output= 0
Output Increment Type= 1
Profile and TS Output Increment= 1
Transport Output Increment 1
XS Output Flag= 0
XS Output Increment= 10
Read HDF5 Sediment Hotstart= 0
Sediment Hotstart Type= 0
Write Gradation File= 0
Read Gradation Hotstart= 0
Write HDF5 File= 1
Write Binary Output= 1
Write DSS Sediment File= 0
DSS Sediment Output Type= 1
SV Curve= 0
Specific Gage Flag= 0
Subcell Erosion Methods= 0
Subcell Deposition Methods= 0
Advection Scheme= 1
Matrix Solver= 0
Implicit Weighting Factor= 1
Maximum Outer Loop Convergence Iterations= 5
Convergence Maximum Absolute= 0.001
Convergence RMSE= 0.0001
Grain Fractions Max Abs Error= 0.001
Max Subgrid Regions= 1
Max Subgrid Length Scale= 3.402823E+38
Initial Layer Thickness= 3.402823E+38
Min Layer Thickness= 3.402823E+38
Max Layer Thickness= 3.402823E+38
Number of Layers= 5

--- BIGRN.f01 (steady flow) ---

Flow Title=Flow
Program Version=6.30
Number of Profiles= 1
Profile Names=F01pct
River Rch & RM=BIGRN,Main,11981
     643
River Rch & RM=BIGRN,Main,11000
     715
River Rch & RM=BIGRN,Main,7999
    1010
River Rch & RM=BIGRN,Main,7211
    1170
River Rch & RM=BIGRN,Main,3999
    1330
Boundary for River Rch & Prof#=BIGRN,Main            , 1
Up Type= 0
Dn Type= 3
Dn Slope=0.00733
DSS Import GetInterval= 0
DSS Import GetPeak= 0
DSS Import FillOption= 0

--- BIGRN.g01 (geometry) ---

Geom Title=Geometry
Program Version=6.30

River Reach=BIGRN           ,Main
Reach XY= 30
     1669492.673      406149.2941669379.77566647405797.929800029
      1669581.15      405407.801     1669408.689        405204.8
     1669389.376      405103.749     1669264.073      404997.757
      1669270.36      404936.677     1669206.137      404853.591
     1668829.327      404561.6651668448.31504532404335.307420969
     1668270.176      404119.733      1667627.49      403786.039
     1667618.094      403703.941     1667495.647        403606.5
     1667075.417      403076.757     1666661.798      402768.627
     1665837.434      402046.015     1665576.156      401698.794
     1665185.244      401018.435     1665101.313      400658.854
     1665007.897      400521.172      1664946.96      400256.732
      1664972.83      399902.037     1664908.731      399318.257
     1664963.057      398693.948     1665113.098      398367.134
     1665124.595      398243.537     1664971.105      397225.442
1664771.19265738      396564.917     1664702.119      396452.062

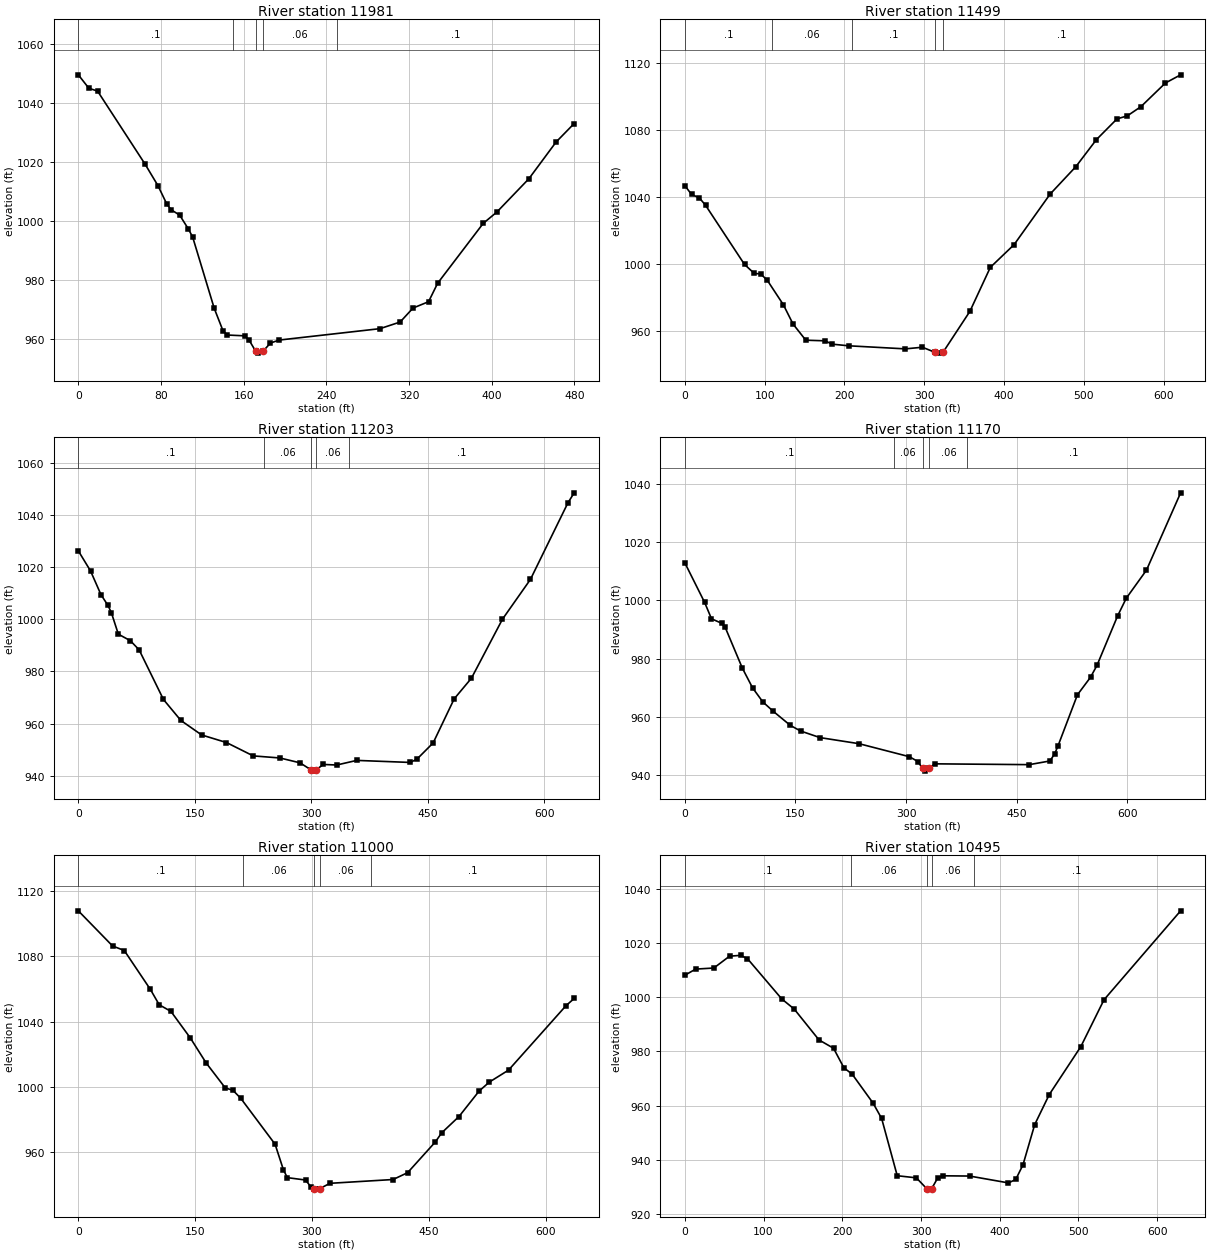
Type RM Length L Ch R = 1 ,11981   ,482.3,482.3,482.3
XS GIS Cut Line= 3
1669657.85376764406093.5821433611669339.35085168406191.327932144
1669277.83462066 406324.40881977
#Sta/Elev= 30
       0 1049.47    10.2 1044.91    18.6 1043.96    64.6 1019.16    77.1 1011.84
    85.5 1005.71    89.7 1003.73    98.1 1001.86   106.4  997.21   110.6  994.48
   131.5  970.26   139.9  962.73   144.1   961.2   160.8  960.93     165  959.61
   171.6955.7125   173.4  955.06   178.7  955.68   185.9  958.48   194.3  959.49
   291.9  963.36   311.4  965.61   323.9  970.36   338.9   972.5   347.7  978.77
   391.8  999.08     405 1002.92     436 1014.22   462.3 1026.67   479.8 1032.95
#Mann= 5 ,-1,0
       0      .1       0     150     .06       0   171.6    .045       0
   178.7     .06       0     250      .1       0
Bank Sta=171.6,178.7
XS Rating Curve= 0 ,0
Exp/Cntr(USF)=0,0
Exp/Cntr=0.3,0.1

Type RM Length L Ch R = 1 ,11499   ,296,296,296
XS GIS Cut Line= 6
1669718.09251826405780.1756143421669620.21312083405765.271116585
1669530.77760418405749.7576961671669458.87814167405727.756427839
1669364.75004908405693.9162724171669125.66850625405601.698281005
#Sta/Elev= 30
       0 1046.68     8.4 1041.41    18.2 1039.35      26 1034.92    74.8  999.59
      87  994.25    95.1  993.89   103.2  990.24   123.5  975.52   135.6  964.01
   151.6  954.36   175.8  953.99   184.4  952.01   205.1  951.02   276.4  949.18
   297.7  950.16   313.4  947.13   318.9  946.64   323.5947.1288   357.2  971.59
   382.8  997.86   412.6 1011.44   457.7 1041.59     490 1058.01   515.7 1074.12
   541.5  1086.5   554.3 1088.27   571.5 1093.81   602.2 1107.94   621.2  1112.8
#Mann= 5 ,-1,0
       0      .1       0  109.01     .06       0  209.78      .1       0
   313.4    .045       0   323.5      .1       0
Bank Sta=313.4,323.5
XS Rating Curve= 0 ,0
Exp/Cntr(USF)=0,0
Exp/Cntr=0.3,0.1

Type RM Length L Ch R = 1 ,11203   ,32.2,32.2,32.2
XS GIS Cut Line= 4
1669755.91200655405654.5949722551669680.25800101405503.286961183
1669412.55921219405397.8078188491669248.88468098405476.371593829
#Sta/Elev= 30
       0 1026.18    15.7  1018.5    29.1 1009.43    38.1 1005.29    42.5 1002.54
    51.5  994.27      67  991.75    78.3  988.25   109.6  969.24     132  961.21
   158.8  955.64   190.8  952.73   225.2  947.62   259.6  946.82   285.5  944.96
   299.3  942.33   302.6  941.78   306.4  942.33   315.5  944.34   332.7  944.12
   358.5  945.89   427.3  945.11   435.9  946.33   456.9  952.58     484  969.48
   506.2  977.38   546.2 1000.01   582.2 1015.25   630.4 1044.54   638.5 1048.42
#Mann= 5 ,-1,0
       0      .1       0  239.17     .06       0   299.3    .045       0
   306.4     .06       0  349.17      .1       0
Bank Sta=299.3,306.4
XS Rating Curve= 0 ,0
Exp/Cntr(USF)=0,0
Exp/Cntr=0.3,0.1

Type RM Length L Ch R = 1 ,11170   ,170.8,170.8,170.8
XS GIS Cut Line= 4
1669798.83110584405635.6814708711669705.71848364405477.826478551
1669419.10619344405370.1650091341669253.24933515405447.273899392
#Sta/Elev= 30
       0 1012.89    26.9  999.29    36.2  993.68    50.1  992.14    54.7   990.8
      78  976.79    91.9  970.02   105.8   965.2   119.8  962.01     143  957.17
   156.9  955.24   183.3  952.97   236.3  950.88   304.6  946.42     316  944.77
  322.31  942.42     326  941.48   331.5  942.42   338.8  943.98     467   943.7
   495.1  944.96   501.6  947.45     506   950.1   532.4  967.65   550.1  973.64
   558.9  977.72   586.8  994.64   598.6 1000.73     626 1010.36   672.3 1036.85
#Mann= 5 ,-1,0
       0      .1       0  283.27     .06       0  322.31    .045       0
   331.5     .06       0  383.27      .1       0
Bank Sta=322.31,331.5
XS Rating Curve= 0 ,0
Exp/Cntr(USF)=0,0
Exp/Cntr=0.3,0.1

Type RM Length L Ch R = 1 ,11000   ,505,505,505
XS GIS Cut Line= 6
1669739.37725259 405106.222237841669664.28061801 405162.32875292
1669533.88061634405259.2927978341669393.44946675405363.715489253
 1669303.5454471405400.5913997591669198.01875526405425.394827843
#Sta/Elev= 30
       0 1107.77      44 1086.25      59 1083.49    92.6 1059.63   103.9 1050.27
   118.9 1046.24   143.8    1030   164.1 1014.72   188.7   999.4   198.6  997.93
   208.6  993.04   252.7  964.93   263.4  949.28   268.4  944.49   291.8  943.03
   298.5  938.97   302.5 937.736   305.3  937.46   309.9  937.73   323.2  941.02
   404.2  943.34   422.9  947.52   458.6  966.38   466.6  971.87   488.9   981.9
   514.8  997.51   527.9 1002.98   552.5 1010.28   626.4 1049.76   636.8 1054.13
#Mann= 5 ,-1,0
       0      .1       0  211.24     .06       0   302.5    .045       0
   309.9     .06       0  376.24      .1       0
Bank Sta=302.5,309.9
XS Rating Curve= 0 ,0
Exp/Cntr(USF)=0,0
Exp/Cntr=0.3,0.1

Type RM Length L Ch R = 1 ,10495   ,495.5,495.5,495.5
XS GIS Cut Line= 6
  1669478.749493404707.1492170841669282.77285084404872.961549506
1669200.46855351404930.2891907541669128.13306826404960.019118175
1669046.50527875405006.7670561671668963.79350193405063.730196834
#Sta/Elev= 30
       0 1008.06    13.8 1010.33    36.9 1010.73    56.8 1015.09      71  1015.4
    79.6 1014.17   123.2  999.31   138.9  995.62   170.4  984.23   188.9  981.16
     202  973.98   212.6  971.58   239.1  960.94     250  955.27   269.8  934.17
   294.1  933.39   307.1929.4377     310  929.23   313.6  929.44   321.5   933.5
   328.2  934.14   361.7  934.05   411.1  931.52   420.3   932.8   429.5  938.19
   444.4  953.03   462.9   964.1     503  981.78   532.4  999.03   629.7 1031.81
#Mann= 5 ,-1,0
       0      .1       0   211.7     .06       0   307.1    .045       0
   313.6     .06       0  367.02      .1       0
Bank Sta=307.1,313.6
XS Rating Curve= 0 ,0
Exp/Cntr(USF)=0,0
Exp/Cntr=0.3,0.1

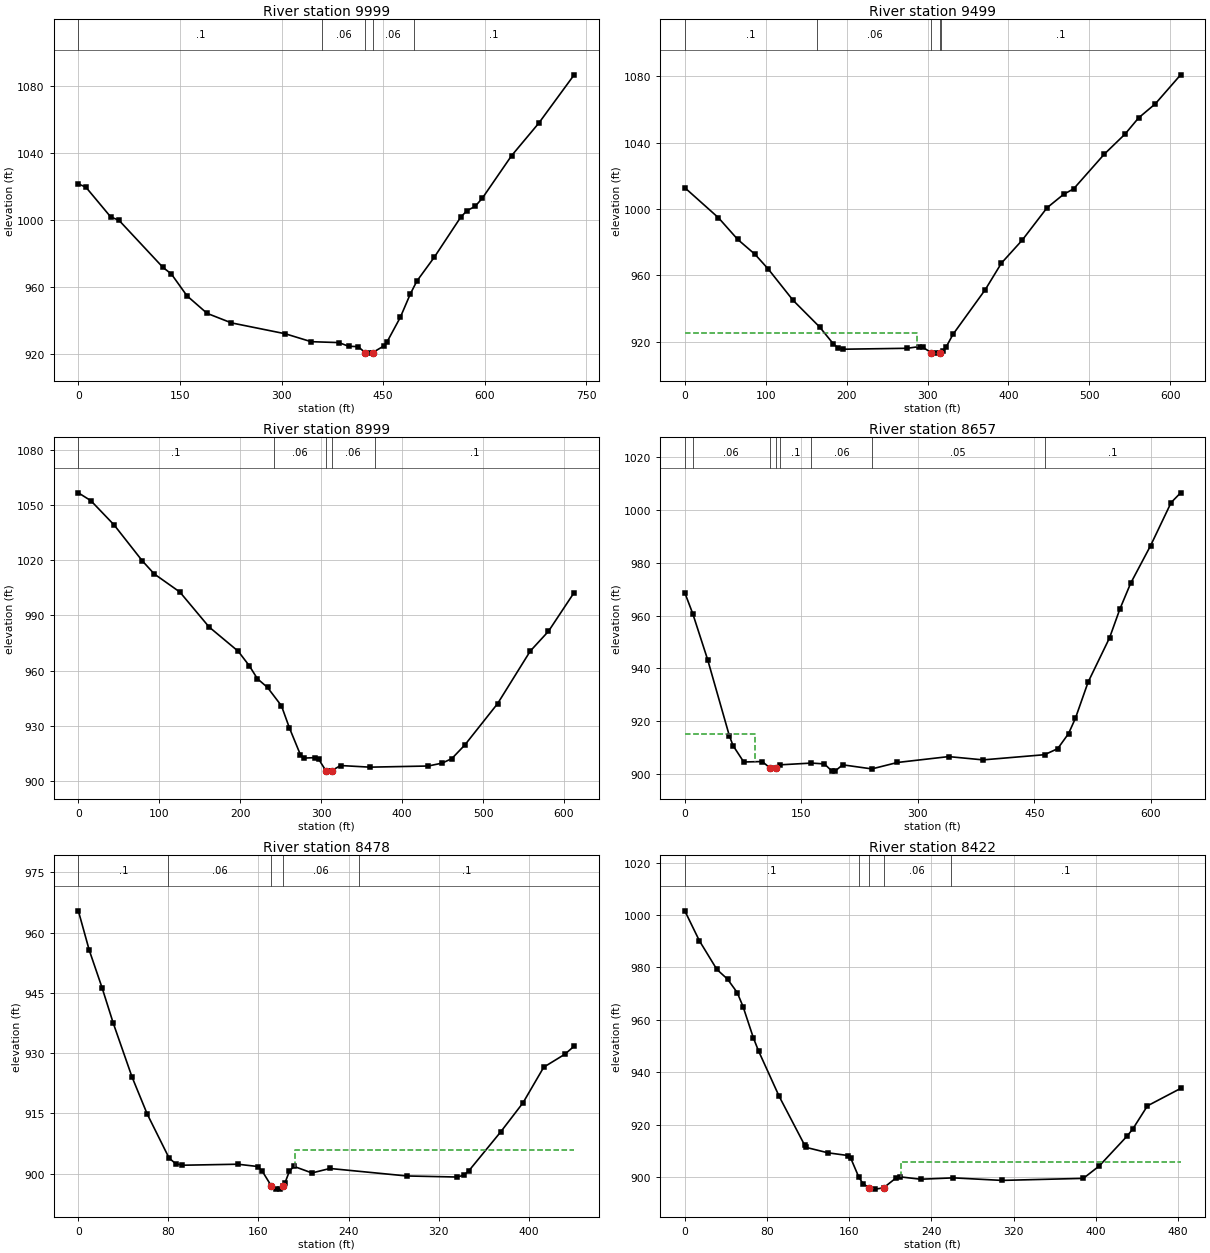
Type RM Length L Ch R = 1 ,9999    ,499.9,499.9,499.9
XS GIS Cut Line= 6
1669219.13795382404397.1214007551669009.65266217404435.064459428
1668830.01949126404626.4751658441668779.52188884 404681.93994993
1668721.56268717404747.5438213351668664.16844501404822.249380589
#Sta/Elev= 30
       0  1021.5    11.2 1019.51    47.8  1001.8      60  999.81     125  971.71
   137.2   967.9   160.4  954.82   190.1  944.37   225.9   938.7   305.6   932.2
   343.7  927.49   384.7  926.95     399  924.77   413.1  924.54   423.4  921.02
   430.1  920.67   434.7921.0173   450.8  924.88   455.6  927.19   475.4  941.98
   490.1  955.84   499.8  963.56   525.8  977.93   564.5 1001.59   573.7 1005.51
   585.8 1008.06   596.6 1013.02   639.7  1038.3   679.7 1057.59   732.1 1086.46
#Mann= 5 ,-1,0
       0      .1       0  360.39     .06       0   423.4    .045       0
   434.7     .06       0  495.39      .1       0
Bank Sta=423.4,434.7
XS Rating Curve= 0 ,0
Exp/Cntr(USF)=0,0
Exp/Cntr=0.3,0.1

Type RM Length L Ch R = 1 ,9499    ,500.3,500.3,500.3
XS GIS Cut Line= 6
1668638.98411217404092.6324015111668575.10792759404161.544993341
 1668520.0824471404229.5773375931668472.91718709404287.890541166
1668307.83943325404491.9875739221668248.88285826404564.879160419
#Sta/Elev= 30
       0 1012.88    41.6  994.74    65.3  981.71    86.9  972.61     103  963.87
   133.8  944.93   166.5   928.9   183.5  918.68   189.2  916.26   195.6  915.42
   274.6  915.98   289.5  916.97   294.5  916.46   304.7 913.315   308.7  913.06
   315.1913.3113     319   914.3   322.9  916.73   331.4  924.38   371.3  951.36
   391.3   967.4   416.8  981.15   447.6 1000.76   468.2 1008.92   480.4 1012.14
   518.5 1033.18     544 1045.22   560.8 1055.03   581.4 1063.48   612.7 1080.99
#Mann= 5 ,-1,0
       0      .1       0  163.96     .06       0   304.7    .045       0
   315.1     .06       0  316.46      .1       0
#XS Ineff= 2 , 0
          287.35  925.15
Permanent Ineff=
       F       F
Bank Sta=304.7,315.1
XS Rating Curve= 0 ,0
Exp/Cntr(USF)=0,0
Exp/Cntr=0.3,0.1

Type RM Length L Ch R = 1 ,8999    ,342,342,342
XS GIS Cut Line= 6
1668211.26777601 403741.296161921668092.84937768403968.480418846
1668046.43411617 404057.061934591668011.85938217404123.641197756
1667971.64981693404201.3871052561667928.62332818404284.716663003
#Sta/Elev= 30
       0 1056.59    15.5 1052.32    44.3 1039.08    78.9  1019.7    93.7 1012.54
   125.4 1002.69   161.5  983.71   197.5  970.51   211.2  962.63   221.2  955.59
   233.7  950.84   250.9  940.89   260.8  928.81   274.3  914.32   278.8  912.46
   292.4  912.72   296.9  911.85   305.7905.6806   310.1  905.38   313.1  905.67
     324  908.42   360.1  907.54   432.2  908.16   449.5  909.74   461.4   912.2
   477.3  919.51   517.9  942.04   558.3  970.62   580.8  981.38   612.5 1002.42
#Mann= 5 ,-1,0
       0      .1       0  241.21     .06       0   305.7    .045       0
   313.1     .06       0   366.2      .1       0
Bank Sta=305.7,313.1
XS Rating Curve= 0 ,0
Exp/Cntr(USF)=0,0
Exp/Cntr=0.3,0.1

Type RM Length L Ch R = 1 ,8657    ,178.6,178.6,178.6
XS GIS Cut Line= 3
1667831.94165879403751.7962327771667651.32839914 404043.17232017
1667775.06344995404311.597551365
#Sta/Elev= 30
       0  968.62    10.3  960.65    29.5  943.21    57.3  914.52    62.1  910.74
    75.9  904.52    99.7  904.69   109.1  902.41   117.4902.3995   122.4  903.44
   163.1  904.11   179.7  903.79   189.5  901.06   193.8  901.14   203.2  903.45
   240.9   901.9   273.8  904.34   339.7  906.56     384  905.32   463.2  907.28
   480.1  909.56   494.1  915.28   502.9  921.05   519.3  934.79   546.9  951.55
   560.1  962.38     574  972.17   599.8   986.5   626.2 1002.79   638.4 1006.46
#Mann= 8 ,-1,0
       0      .1       0    10.3     .06       0   109.1    .045       0
   117.4     .06       0   122.4      .1       0   163.1     .06       0
   240.9     .05       0   463.2      .1       0
#XS Ineff= 2 , 0
              90     915
Permanent Ineff=
       F       F
Bank Sta=109.1,117.4
XS Rating Curve= 0 ,0
Exp/Cntr(USF)=0,0
Exp/Cntr=0.3,0.1

Type RM Length L Ch R = 1 ,8478    ,56.3,56.3,56.3
XS GIS Cut Line= 5
1667749.11900381403691.9244339971667677.27284528403785.723585419
 1667640.3519027403767.7620457851667490.67240575403773.749225663
1667401.86257089403870.541967023
#Sta/Elev= 30
       0  965.42     9.7  955.61    21.1  946.26      31  937.47    47.7  924.05
    61.2  914.82    80.6  903.88    86.4  902.48    92.5  902.09   141.7  902.34
   159.4  901.77   163.5  900.55   171.5  896.89   175.5  896.14   179.5  896.15
   181.5   896.9   183.5  897.65   187.5  900.62   191.5   901.8   207.5  900.17
   223.5  901.28   291.6  899.42   336.5  899.15   342.4  899.62   346.8  900.68
   375.1  910.37   394.9   917.6   413.4   926.5   432.2  929.73   440.4  931.73
#Mann= 5 ,-1,0
       0      .1       0      80     .06       0   171.5    .045       0
   181.5     .06       0  249.21      .1       0
#XS Ineff= 1 ,-1
  192.31440.3726  905.98
Permanent Ineff=
       F
Bank Sta=171.5,181.5
XS Rating Curve= 0 ,0
Exp/Cntr(USF)=0,0
Exp/Cntr=0.3,0.1

Type RM Length L Ch R = 1 ,8422    ,422.5,422.5,422.5
XS GIS Cut Line= 5
1667759.09763694403635.5451568131667687.25147841403729.344308235
1667650.33053583403711.3827686011667500.65103888403717.369948479
1667381.90530463403844.098589229
#Sta/Elev= 30
       0 1001.62    14.2  990.19    31.2  979.26    41.6  975.54      51  970.44
    56.7  965.07    66.8  953.08    71.8  948.12    91.9  930.77   116.7  912.14
   118.2   911.3   139.4  909.24   159.2  908.19   161.4  907.33   169.4  899.97
   173.4  897.51   179.3895.8795   185.6  895.38   193.5  895.88   205.5   899.6
   209.5  900.07   229.5  899.16   261.5  899.68   308.7  898.71     388  899.49
   403.4   904.2   430.5  915.59   436.1  918.32   450.4  927.17   482.7  933.82
#Mann= 5 ,-1,0
       0      .1       0  169.21     .06       0   179.3    .045       0
   193.5     .06       0  259.21      .1       0
#XS Ineff= 2 , 0
                          210.64          905.89
Permanent Ineff=
       F       F
Bank Sta=179.3,193.5
XS Rating Curve= 0 ,0
Exp/Cntr(USF)=0,0
Exp/Cntr=0.3,0.1

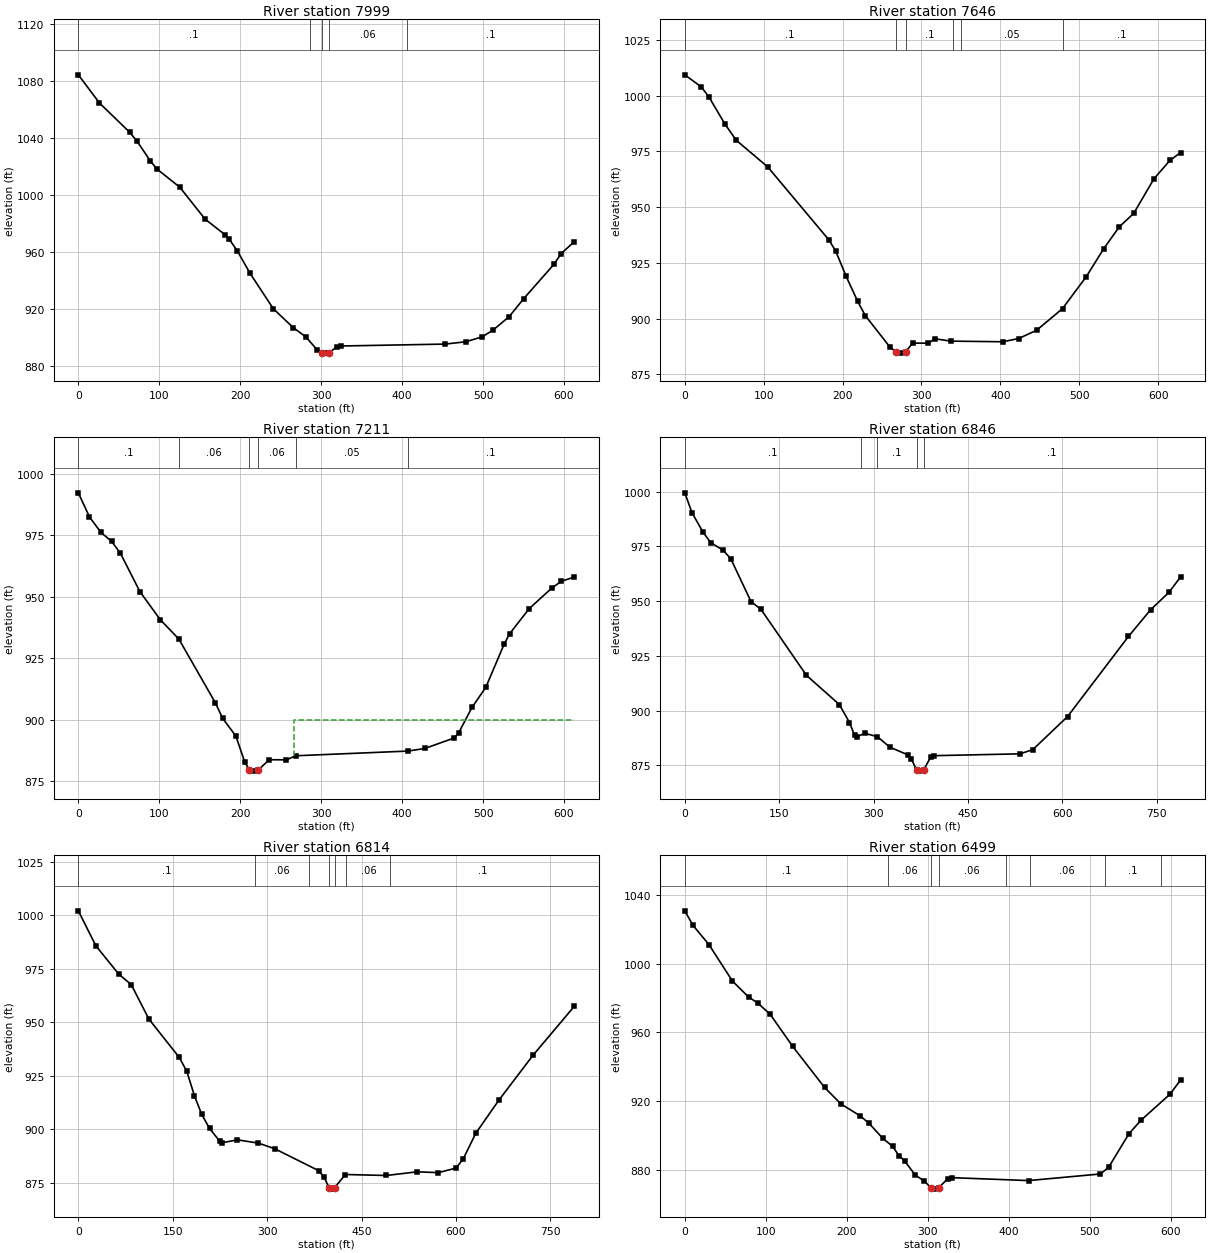
Type RM Length L Ch R = 1 ,7999    ,353.4,353.4,353.4
XS GIS Cut Line= 6
1667578.91241342403230.9034819161667503.00410068403285.960130334
1667371.42857642  403381.38972951667290.47499818 403440.09696117
1667229.77892534403484.1227917521667083.09352317403590.514311254
#Sta/Elev= 30
       0 1084.23    26.1 1064.45    63.3 1043.96    72.6 1037.55    89.1 1023.62
    97.3 1017.98   125.4 1005.26   156.6  982.85   181.3  971.88   186.3  968.82
   196.2  960.73   212.2  944.75   240.9  919.92   265.3  906.72     281   900.2
   295.3  890.87     301  889.05   304.9  888.75   309.8  889.05   319.7  893.32
   323.9  893.75   453.1   895.1   478.6  896.72   498.7  900.18   512.4  904.96
   532.2  914.36   550.2  927.02   587.4  951.04   596.4  958.62   612.5  966.96
#Mann= 5 ,-1,0
       0      .1       0  286.31     .06       0     301    .045       0
   309.8     .06       0  406.31      .1       0
Bank Sta=301,309.8
XS Rating Curve= 0 ,0
Exp/Cntr(USF)=0,0
Exp/Cntr=0.3,0.1

Type RM Length L Ch R = 1 ,7646    ,435.5,435.5,435.5
XS GIS Cut Line= 2
1667341.08782623402966.4059771181666833.28627362403336.724139939
#Sta/Elev= 30
       0 1009.35      21 1003.91    30.9  999.25    50.7  987.38    65.2  980.01
   105.2  968.02   182.6  935.35   191.2  930.41   204.2  919.24     219  907.85
   228.9  901.32   259.9  887.34   267.3885.1118   273.5  884.55   279.9  885.13
   288.7  889.04   308.6  889.02   317.1  890.99   337.2  889.93     403  889.65
   423.1  891.09     446  894.81   478.8  904.53     509  918.88   530.9  931.33
   550.7  941.15   569.1  947.25   594.8  962.79   615.1  971.01   628.5  974.51
#Mann= 6 ,-1,0
       0      .1       0   267.3    .045       0   279.9      .1       0
     340     .06       0     350     .05       0     480      .1       0
Bank Sta=267.3,279.9
XS Rating Curve= 0 ,0
Exp/Cntr(USF)=0,0
Exp/Cntr=0.3,0.1

Type RM Length L Ch R = 1 ,7211    ,364.7,364.7,364.7
XS GIS Cut Line= 6
1666941.48695736402686.5187962541666877.47100927402755.011769493
 1666817.6223757 402818.844318991666766.08245252402873.329118166
1666585.69304952403064.0278837421666521.26798153403132.134374831
#Sta/Elev= 30
       0  992.16    13.7  982.38    27.9  976.08    41.1  972.42      52  967.57
      76  952.04   101.3  940.54   124.1  932.74   169.4  906.73   178.1  900.56
   194.6  893.27   205.6  882.68   211.3879.4471   216.6  879.01   222.1  879.44
   235.8  883.64   257.1   883.6   268.4  885.25     407  887.16   427.9  888.21
   464.4   892.5   469.9  894.64   486.4  904.96   503.3  913.05   525.9  930.55
   532.7  934.84     557  945.08   585.1  953.52   596.7  956.19   612.5  957.91
#Mann= 6 ,-1,0
       0      .1       0   124.1     .06       0   211.3    .045       0
   222.1     .06       0   268.4     .05       0     407      .1       0
#XS Ineff= 2 , 0
                          266.99          899.92
Permanent Ineff=
       F       F
Bank Sta=211.3,222.1
XS Rating Curve= 0 ,0
Exp/Cntr(USF)=0,0
Exp/Cntr=0.3,0.1

Type RM Length L Ch R = 1 ,6846    ,32.1,32.1,32.1
XS GIS Cut Line= 3
1666844.95969771402536.940133503  1666560.014285402560.223610807
1666236.26307679402943.846617801
#Sta/Elev= 30
       0  999.42    11.5  990.31    28.9  981.49      41  976.73      61  973.18
    73.1   969.3   105.2  949.76   121.2  946.14   193.3  916.06   245.7  902.68
   261.7  894.52   269.7  888.71   273.8  888.06   285.9  889.56   305.9  888.08
   325.8  883.27   354.3  879.75   360.2  877.76   368.4  872.79   372.6  872.31
   379.4  872.78     391  878.84   396.2  879.37     533  880.21   553.2  882.18
   608.2  897.23     705  933.81   740.2  946.02   769.5  954.01   787.9  961.05
#Mann= 5 ,-1,0
       0      .1       0     280     .06       0   305.9      .1       0
   368.4    .045       0   379.4      .1       0
Bank Sta=368.4,379.4
XS Rating Curve= 0 ,0
Exp/Cntr(USF)=0,0
Exp/Cntr=0.3,0.1

Type RM Length L Ch R = 1 ,6814    ,314.3,314.3,314.3
XS GIS Cut Line= 3
1666839.97038115402493.1450214331666555.02496844402516.428498736
1666231.27376022402900.051505731
#Sta/Elev= 30
       0 1002.06    27.9  985.71    64.1  972.55    84.1  967.59   112.2  951.47
   160.4  933.61   172.4  927.09   184.5  915.67   195.9   907.1   208.5  900.44
   224.6   894.5   228.6  893.75   252.7   895.1   285.9   893.6   312.2  890.94
   381.7  880.75   390.2  877.87   398.5872.7534   401.2  872.09   407.3  872.78
   424.3  878.92   489.6  878.46   538.5  880.18   571.9  879.79   600.1   881.9
   611.6   886.2   631.5  898.13   668.1  913.58   722.3  934.53   787.9  957.39
#Mann= 7 ,-1,0
       0      .1       0     280     .06       0   365.9      .1       0
   398.5    .045       0   407.3      .1       0   425.9     .06       0
   495.9      .1       0
Bank Sta=398.5,407.3
XS Rating Curve= 0 ,0
Exp/Cntr(USF)=0,0
Exp/Cntr=0.3,0.1

Type RM Length L Ch R = 1 ,6499    ,500,500,500
XS GIS Cut Line= 6
1666418.02825226402156.8183597621666362.98571143402232.708956003
1666267.57973425402364.2533123341666208.86758134402445.203281671
1666113.46226034402576.7479660961666056.95745209402651.578197002
#Sta/Elev= 30
       0  1030.7    10.1 1022.27    29.8 1011.07    58.9  989.82    78.7  980.63
      90  977.11   105.5  970.52   133.1  951.97   172.6  928.03   193.1  918.31
     216  911.67     227  907.43   244.6  898.37   256.6  893.79   264.7  888.25
   271.4  885.41   284.7     877   296.1  873.54   304.1869.5767   307.6  868.87
   313.4  869.57   324.8  874.94   330.5  875.53   424.6  873.84   513.5  877.69
   523.5  881.52   548.6  901.02   563.6  908.96   599.5  924.12   612.5  932.38
#Mann= 8 ,-1,0
       0      .1       0  251.25     .06       0   304.1    .045       0
   313.4     .06       0  396.25     .05       0  426.25     .06       0
  518.75      .1       0  588.75     .05       0
Bank Sta=304.1,313.4
XS Rating Curve= 0 ,0
Exp/Cntr(USF)=0,0
Exp/Cntr=0.3,0.1

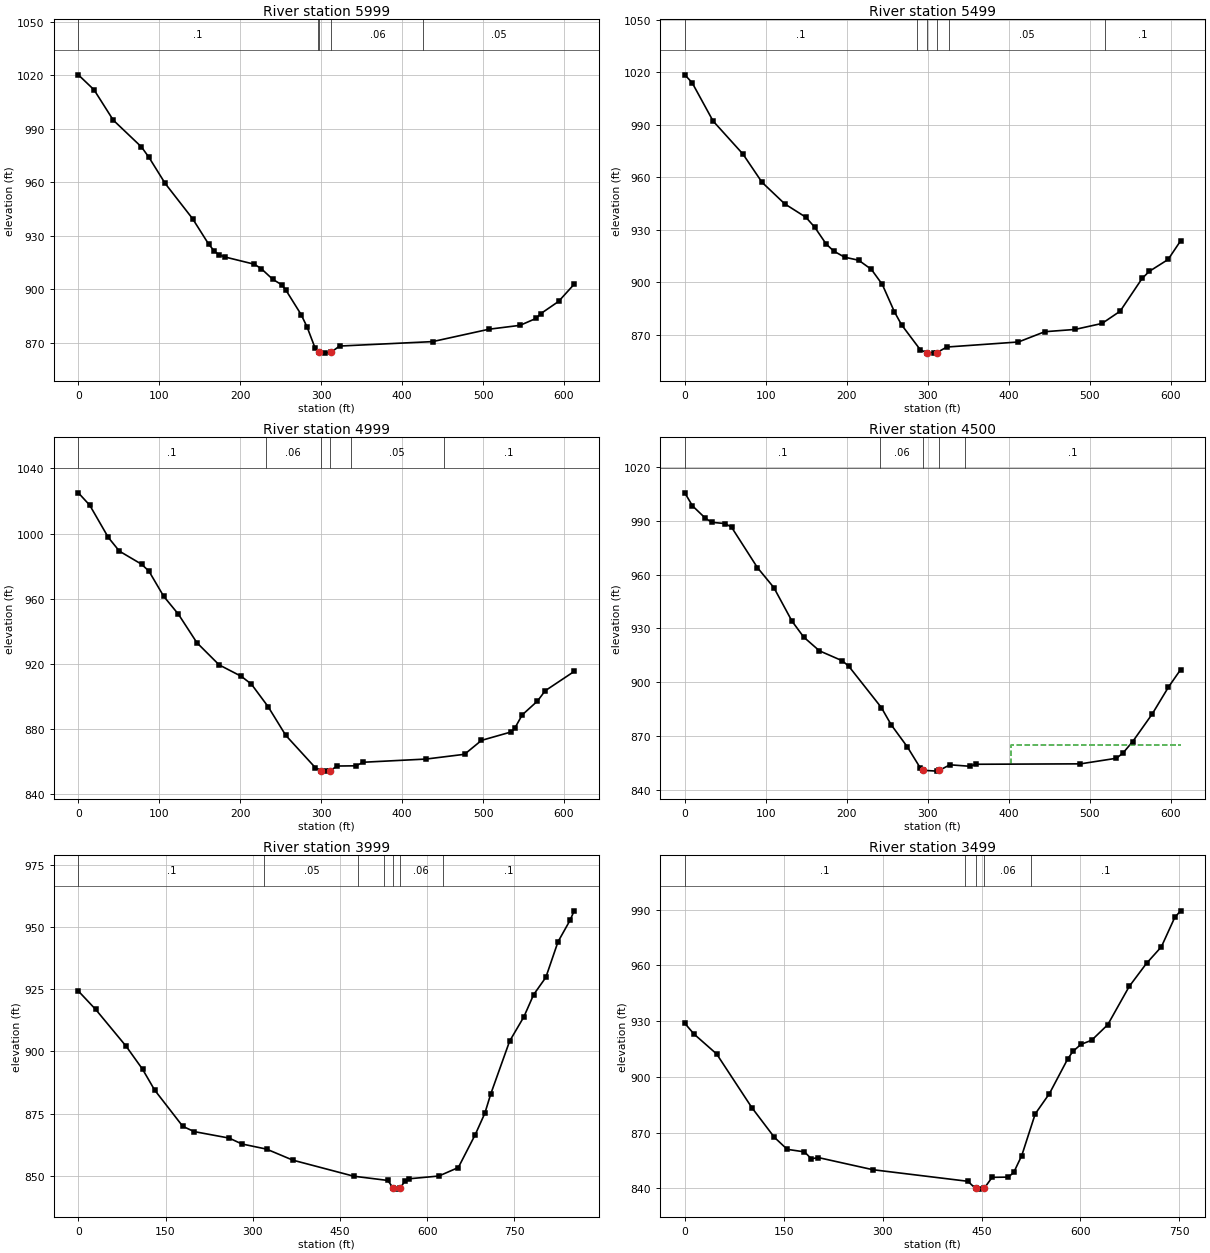
Type RM Length L Ch R = 1 ,5999    ,500,500,500
XS GIS Cut Line= 6
1666085.83764367401862.7949976771666017.92898685401927.428398594
1665954.54755193401987.7524249261665900.22023275402039.458358258
1665773.45670676402160.1070670931665642.16563076402285.064494342
#Sta/Elev= 30
       0 1020.22    19.4 1011.83    43.1  994.85      78  979.79    87.3  973.92
   107.3  959.32   141.1  939.61   160.9  925.38     168  921.42   173.6  919.39
   181.2  918.11   217.5  914.05     226  911.56   240.1  905.63   251.4  902.49
   256.4  899.55   275.2  885.86   282.6  878.85   292.6  866.93   296.7  864.82
   305.2  864.23   312.5864.8171   322.7  868.19   437.7  870.69   507.3  877.63
   545.7  879.81   565.5  883.71   571.1  886.31   593.2  893.19   612.5  902.84
#Mann= 5 ,-1,0
       0      .1       0  296.25     .06       0   296.7    .045       0
   312.5     .06       0  426.25     .05       0
Bank Sta=296.7,312.5
XS Rating Curve= 0 ,0
Exp/Cntr(USF)=0,0
Exp/Cntr=0.3,0.1

Type RM Length L Ch R = 1 ,5499    ,500,500,500
XS GIS Cut Line= 6
1665826.08061726401519.9531636691665745.55321926 401567.95733276
1665670.39523309401612.763017416  1665605.973774401651.167140082
1665520.07893267401702.3734025061665299.97307368401833.589019343
#Sta/Elev= 30
       0 1018.43       9 1013.97    34.9  992.05    71.9   973.1    95.4  957.01
   123.4  944.71   149.6  937.03   160.6  931.28   174.6  921.76   183.9  917.74
   197.3  914.23   214.8  912.47   230.5  907.24     244  898.62   258.9  883.04
   267.7  875.62     291  861.26   299.2 859.596   308.2  859.39   311.1   859.6
   323.6  862.87   412.1  865.76   444.7  871.63   481.9  872.92   515.4  876.35
   537.8  883.36   564.9  902.05   573.7  906.09     597   912.9   612.5  923.57
#Mann= 6 ,-1,0
       0      .1       0  286.25     .06       0   299.2    .045       0
   311.1     .06       0  326.25     .05       0  518.75      .1       0
Bank Sta=299.2,311.1
XS Rating Curve= 0 ,0
Exp/Cntr(USF)=0,0
Exp/Cntr=0.3,0.1

Type RM Length L Ch R = 1 ,4999    ,500,500,500
XS GIS Cut Line= 6
1665580.50761759401098.6108305011665498.36276875401143.791514426
1665421.69363075401185.9587529151665355.97755484401222.102709502
1665125.97046892 401348.605409251665043.82496393401393.784780845
#Sta/Elev= 30
       0 1025.06    14.1 1017.45      37   997.7    50.7  989.28    78.1  981.25
    87.2  977.01   105.4   961.6   123.7  950.51   146.5  933.07   173.9   919.5
   201.3  912.46   213.8  907.66   234.4  893.87   256.2  876.27   292.6   856.5
   299.4854.5256   306.3  854.29   310.9  854.53   319.8  857.42   342.8  857.55
     352  859.74   429.6   861.7   477.1  864.62     498  873.15   534.8  878.35
   539.1  880.59   548.3  888.78   567.2   897.3   576.7   903.6   612.5  915.45
#Mann= 6 ,-1,0
       0      .1       0  231.25     .06       0   299.4    .045       0
   310.9     .06       0  336.25     .05       0  451.25      .1       0
Bank Sta=299.4,310.9
XS Rating Curve= 0 ,0
Exp/Cntr(USF)=0,0
Exp/Cntr=0.3,0.1

Type RM Length L Ch R = 1 ,4500    ,500,500,500
XS GIS Cut Line= 6
1665425.43345268 400755.779495181665332.21743175400765.955327839
1665245.23335376400775.5855579231665170.71250543400784.125895172
1664910.39150375400817.8791085031664817.18204451400827.927644834
#Sta/Elev= 30
       0 1005.57     9.4  998.34    25.5  991.37    33.5  989.11    49.6  988.42
    57.7  986.43    89.8  963.79     110  952.71   132.4  933.99   146.9  925.09
   166.3  917.43   194.5  911.88   202.5  908.86   242.8  885.79   254.9   876.2
     275  863.78   291.1  851.94   294.7  850.77   311.3  850.31   314.5850.7627
   327.5  853.84   351.7  853.03   359.7  854.14   488.8  854.37   533.2  857.49
   541.2  860.35   553.3  866.81   577.4  882.17   597.5  897.21   612.5  906.96
#Mann= 5 ,-1,0
       0      .1       0  241.29     .06       0   294.7    .045       0
   314.5     .06       0  346.29      .1       0
#XS Ineff= 2 , 0
                          403.09          864.76
Permanent Ineff=
       F       F
Bank Sta=294.7,314.5
XS Rating Curve= 0 ,0
Exp/Cntr(USF)=0,0
Exp/Cntr=0.3,0.1

Type RM Length L Ch R = 1 ,3999    ,500,500,500
XS GIS Cut Line= 6
1665501.79177657400303.6364698731665169.95332059400266.706982508
1664918.65362634 400342.566410841664846.85422926400364.242220506
1664763.08668026400389.5253064191664673.49565209 400417.14467375
#Sta/Elev= 30
       0  924.29    29.9  916.86    82.2  902.08   110.4  892.85   131.1   884.5
   179.5   869.9   198.9  867.77   259.3  865.15   281.2  862.78   323.7  860.71
   368.9  856.27   473.7  849.81   532.2  848.11   541.6844.9718   545.4  844.62
   553.1  844.97   561.5  847.79   567.9  848.76   619.9  849.89   653.4   853.3
   682.6  866.58     699  875.12   709.1  882.83   741.6  904.12   766.2  913.94
   782.9  922.83   803.9  929.78   824.8  944.08   845.7   952.8   852.6  956.54
#Mann= 7 ,-1,0
       0      .1       0     320     .05       0  481.39      .1       0
  526.39     .06       0   541.6    .045       0   553.1     .06       0
  626.39      .1       0
Bank Sta=541.6,553.1
XS Rating Curve= 0 ,0
Exp/Cntr(USF)=0,0
Exp/Cntr=0.3,0.1

Type RM Length L Ch R = 1 ,3499    ,500,500,500
XS GIS Cut Line= 6
1665363.58995643399924.2462597741665172.24268609399791.025519177
1664915.11557567399843.8636680841664841.64885908399858.951564416
1664755.62180017399875.0171490911664663.31489818   399891.571906
#Sta/Elev= 30
       0  928.81    13.8  923.08    48.3  912.31   101.7  883.45   135.8   867.5
   155.3  861.03   181.5  859.66   191.9  855.94   202.5   856.6   285.4  850.06
   429.3  843.84   440.9839.9683   445.6  839.63   453.8  839.98   466.1  845.98
   490.6  846.09   498.8  848.59     511   857.7   531.4  880.09     553  891.04
   580.6  909.59   588.5  913.69   600.7  917.46     617  919.71   641.4  928.06
   673.9  948.61   700.2  961.07   722.7  969.94     743  985.75   751.9   989.3
#Mann= 5 ,-1,0
       0      .1       0  425.66     .06       0   440.9    .045       0
   453.8     .06       0  525.66      .1       0
Bank Sta=440.9,453.8
XS Rating Curve= 0 ,0
Exp/Cntr(USF)=0,0
Exp/Cntr=0.3,0.1

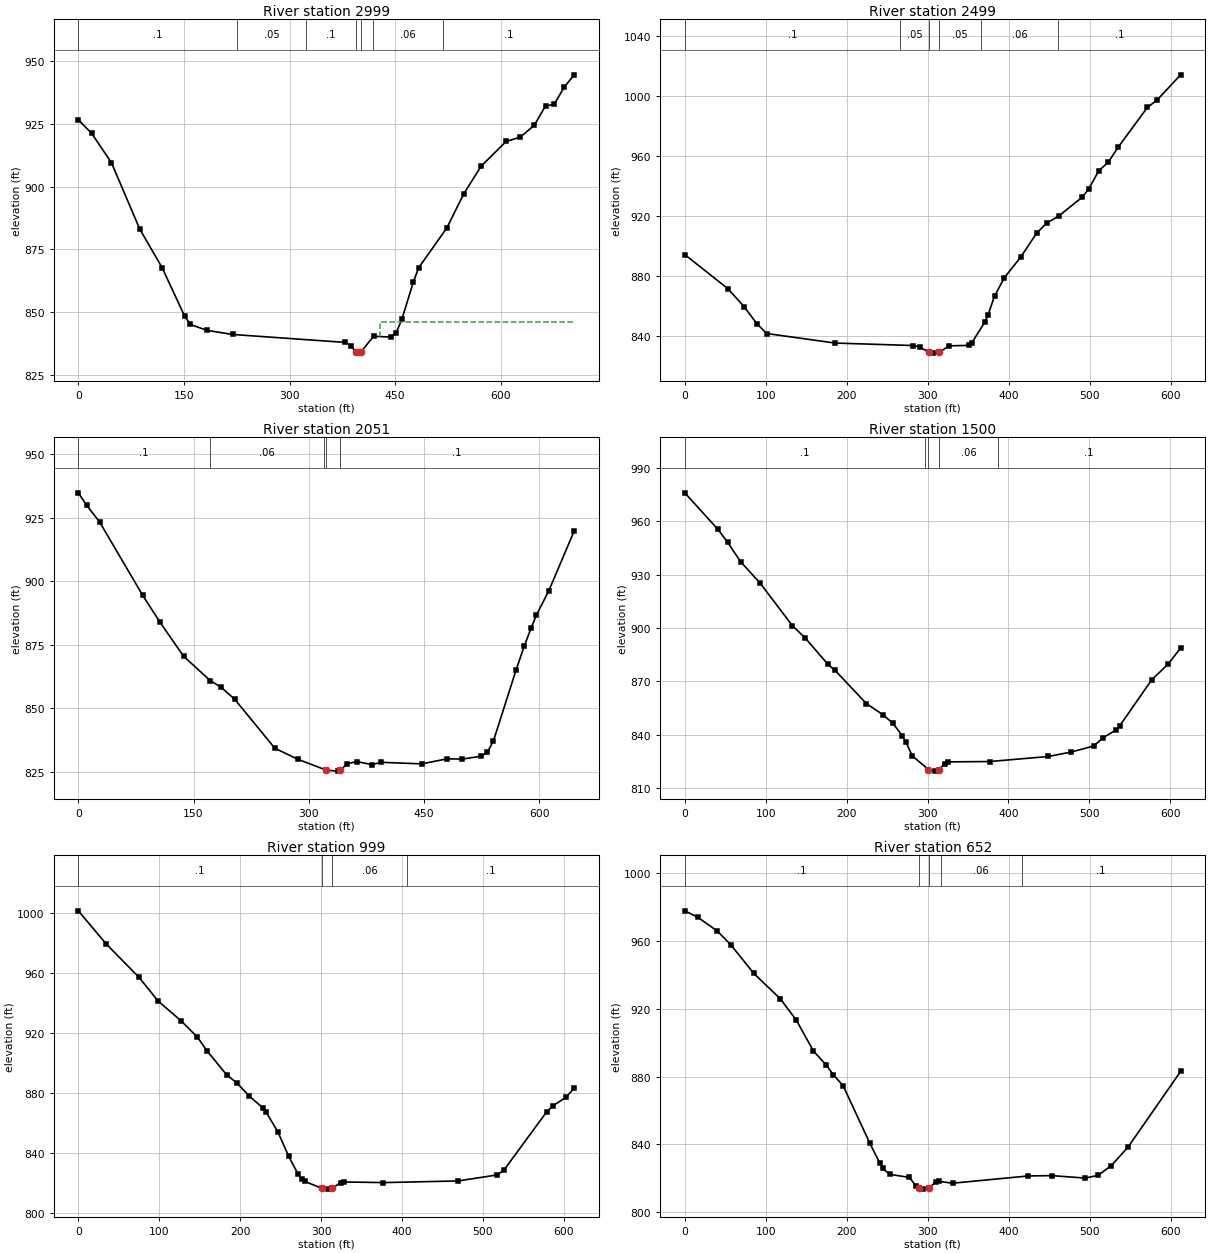
Type RM Length L Ch R = 1 ,2999    ,500,500,500
XS GIS Cut Line= 6
1665307.11163478399322.0756965581665121.86516218399328.874212503
1665034.44243675399332.5484177621664784.66308068399343.048396751
1664697.24002717399346.7219458371664603.57289167 399350.65861775
#Sta/Elev= 30
       0  926.64      19  921.24      47  909.56    87.1  883.19   119.1  867.68
   151.1  848.36   159.1  845.12   182.9  842.77   219.2  841.14   379.3  837.97
   387.3  836.67   393.9 834.187     398  833.71   401.3834.1708   419.3  840.42
   443.3  840.11   451.4  841.84   459.4  847.16   475.9  862.18   483.4  867.76
   523.4  883.63   547.4  897.18     572  908.18   607.5  918.03   627.5  919.73
   647.5  924.47   663.5   932.2   675.6  932.76     690  939.67   704.1  944.56
#Mann= 7 ,-1,0
       0      .1       0  225.37     .05       0  322.87      .1       0
   393.9    .045       0   401.3      .1       0  417.87     .06       0
  517.87      .1       0
#XS Ineff= 2 , 0
                          428.47          846.09
Permanent Ineff=
       F       F
Bank Sta=393.9,401.3
XS Rating Curve= 0 ,0
Exp/Cntr(USF)=0,0
Exp/Cntr=0.3,0.1

Type RM Length L Ch R = 1 ,2499    ,448.4,448.4,448.4
XS GIS Cut Line= 6
1665248.92888442398870.6877929271665155.62329675398861.568716675
1665068.53849718398853.0569226741664993.89396143398845.761333585
1664819.72403418398828.7374175041664639.33364692398811.105234921
#Sta/Elev= 30
       0  894.35    53.1  871.72    73.2  859.74    89.2  848.16   101.3  841.77
   185.7  835.44   282.2  833.78   290.2  832.89   301.6 829.171   306.3  828.72
   314.3  829.18   326.4  833.57   350.5  833.87   354.5  835.54   370.6  849.42
   374.6   854.2   382.6  866.67   394.7  878.94   414.8  892.57   434.7  908.69
   446.9  915.28   461.8     920   491.1  932.67   499.2  938.31   511.2  950.03
   523.3  956.04   535.4  965.97   571.5  992.46   583.6  997.42   612.5 1014.13
#Mann= 6 ,-1,0
       0      .1       0  266.25     .05       0   301.6    .045       0
   314.3     .05       0  366.25     .06       0  461.25      .1       0
Bank Sta=301.6,314.3
XS Rating Curve= 0 ,0
Exp/Cntr(USF)=0,0
Exp/Cntr=0.3,0.1

Type RM Length L Ch R = 1 ,2051    ,551.5,551.5,551.5
XS GIS Cut Line= 6
1665350.21520961398572.9575251171665197.89959214398520.096223996
1665104.63953602398489.3296356981665064.79162059398386.887772554
1664903.93781292398358.7831682391664790.97810213398356.407415262
#Sta/Elev= 30
       0  934.77    10.7  929.91    27.6  923.35    83.7  894.51   105.7  884.14
   137.1  870.48   171.8   860.9   185.4  858.41   203.5  853.62   255.8  834.33
     286  829.95   323.1  825.67   337.5  825.31   340.8  825.64   350.4   828.2
   362.4  829.07   382.2  827.88   394.4  828.78   447.2  828.16   479.7  830.13
     500  830.06   524.3  831.17   532.5  832.66   540.5  837.19   569.9  865.04
   580.5  874.39   589.5  881.52   596.5  886.73   612.5  896.19   645.6  919.74
#Mann= 5 ,-1,0
       0      .1       0  171.23     .06       0  319.43      .1       0
   323.1    .045       0   340.8      .1       0
Bank Sta=323.1,340.8
XS Rating Curve= 0 ,0
Exp/Cntr(USF)=0,0
Exp/Cntr=0.3,0.1

Type RM Length L Ch R = 1 ,1500    ,500,500,500
XS GIS Cut Line= 6
1665377.14778809397886.6576087621665283.27789709397886.000785917
1665195.71114309397885.1156170821665120.67290734 397884.99324201
 1665020.7154301397887.9089185891664764.58274026397895.669729844
#Sta/Elev= 30
       0  975.84      41  955.31      53  948.02      69  937.17      93  925.21
     133  901.29     149  894.28     177  879.54     185  876.55   224.5  857.55
   244.6  851.41     257   846.6     269  839.45     273   836.3   281.1  828.23
   301.1  820.59   309.1   819.7   314.3 820.525   321.1  823.95   325.1  824.88
   377.1  825.09   449.1  827.91   477.1  830.38   505.2  833.77   517.2  838.54
   533.2  842.87   537.2  844.95   577.2  871.08   597.2  879.66   612.7  888.83
#Mann= 5 ,-1,0
       0      .1       0  296.48     .06       0   301.1    .045       0
   314.3     .06       0  386.48      .1       0
Bank Sta=301.1,314.3
XS Rating Curve= 0 ,0
Exp/Cntr(USF)=0,0
Exp/Cntr=0.3,0.1

Type RM Length L Ch R = 1 ,999     ,347.8,347.8,347.8
XS GIS Cut Line= 6
1665294.39401659 397363.11141175  1665039.616639397390.546068177
1664940.19918692397401.3219652621664865.84303643397411.328506917
1664779.19918084 397423.978744091664686.44182043397438.311720669
#Sta/Elev= 30
       0 1001.36    34.5  979.26    74.7  957.19    98.8  941.12     127  928.04
   147.1  917.22   159.2  907.88   183.3  892.06   195.9  886.67   211.5  877.72
   227.6  870.28   232.2  867.14   246.7  853.89   259.8  837.92   271.8  825.63
   275.9  822.68   279.9  821.01   301.2  816.36   308.1  815.88   313.6  816.36
   324.1  820.27   328.2  820.68     377  820.23   469.4  821.34   517.9  825.38
     526  828.64   578.6  867.28   586.7  871.53   602.7  877.07   612.7  883.24
#Mann= 4 ,-1,0
       0      .1       0   301.2    .045       0   313.6     .06       0
  406.25      .1       0
Bank Sta=301.2,313.6
XS Rating Curve= 0 ,0
Exp/Cntr(USF)=0,0
Exp/Cntr=0.3,0.1

Type RM Length L Ch R = 1 ,652     ,215.5,215.5,215.5
XS GIS Cut Line= 6
1665195.48238515397000.3233949431664944.88478924397053.848222274
1664847.09069348397074.7363038551664773.74471157397090.401298765
1664688.17500082397108.6781651121664596.57380607397128.639411274
#Sta/Elev= 30
       0  977.79    15.7   974.1    40.3  965.79    56.6  957.86    85.2  940.88
     118  925.87   137.8  913.23   158.9  895.07   174.9  886.64   183.4  881.12
   195.7  874.46   228.4  840.81   240.7  829.01   244.8  825.75   252.9  822.28
   277.5  820.43   285.7   815.3   289.8  814.09   293.8  813.53   301.4814.0875
   310.2  817.85   314.3   818.1   330.7  817.01   424.3  821.31   453.4   821.5
   494.3  820.07   510.6  821.65     527  827.47   547.5  838.31   612.5     883
#Mann= 5 ,-1,0
       0      .1       0   289.8    .045       0   301.4      .1       0
  316.25     .06       0  416.25      .1       0
Bank Sta=289.8,301.4
XS Rating Curve= 0 ,0
Exp/Cntr(USF)=0,0
Exp/Cntr=0.3,0.1