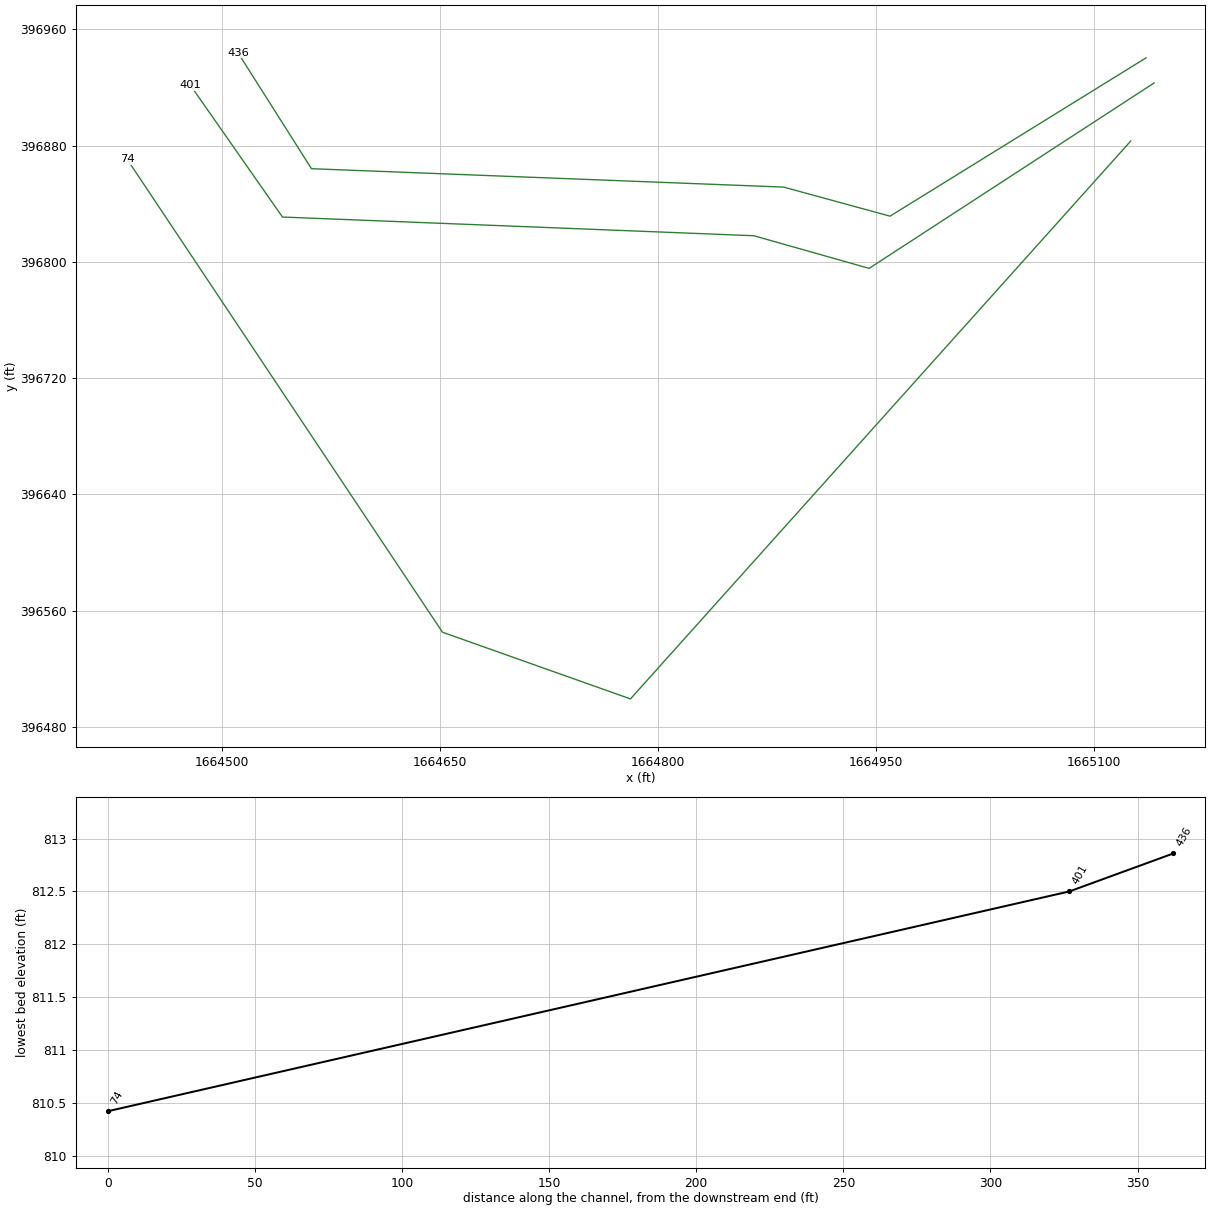
HEC-RAS study BIGRN.prj: BIGRN

--- BIGRN.g01 (geometry) --- (continued)

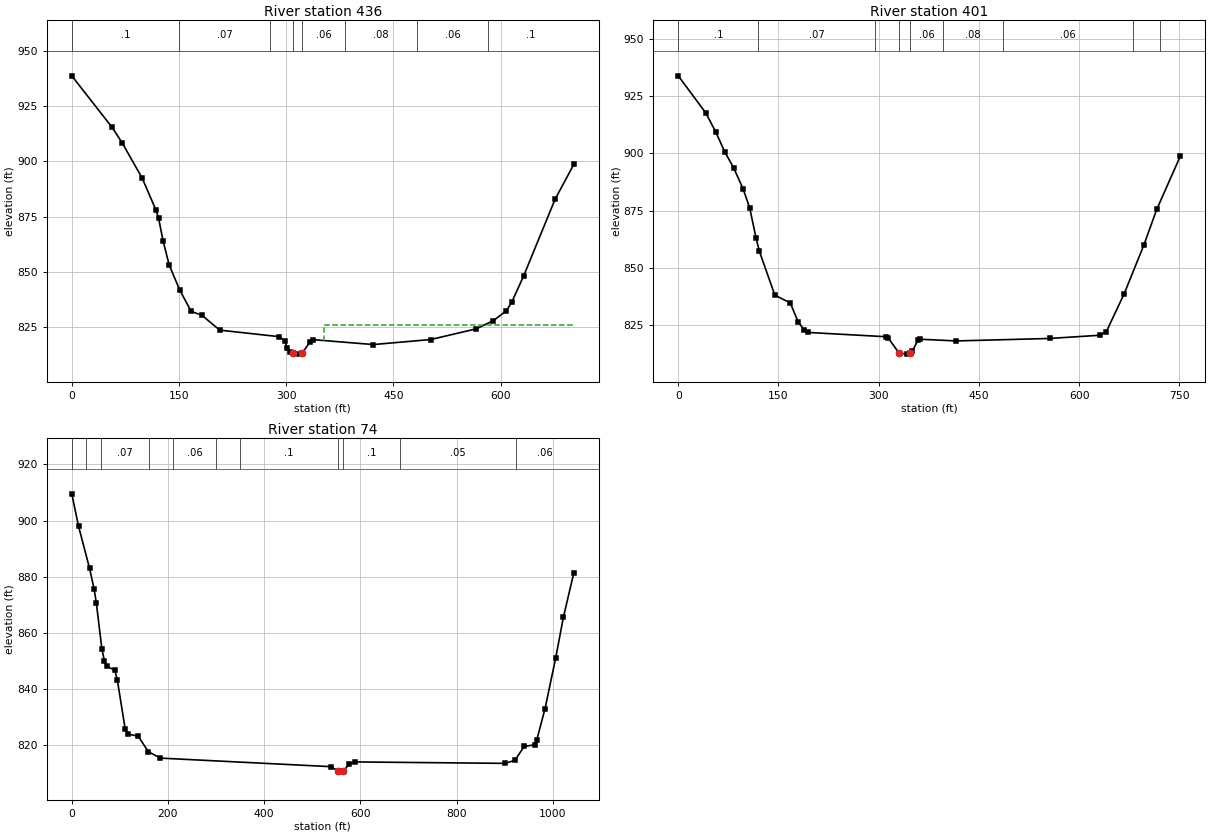
Type RM Length L Ch R = 1 ,436     ,35.4,35.4,35.4
XS GIS Cut Line= 5
1665136.15240463396940.3573903911664959.98467851396831.428845606
1664886.78289506396851.4315411871664561.89265347396864.092238051
1664511.34689952396943.839980501
#Sta/Elev= 30
       0  938.73    56.5  915.39    70.6   908.4    98.7  892.35   117.6  878.18
   121.4  874.47   127.8  864.02   136.4  853.09     151  841.93     167  832.22
   182.2   830.4   207.1  823.71   290.5  820.75   297.7   818.9   301.7  815.65
   305.7  814.03   309.8  813.46   317.7  812.86   322.8813.4697   333.7  818.51
   337.7   819.4   422.1  817.19   502.4  819.47   565.9  824.29   589.9  827.98
   608.1  832.43   615.6  836.31   632.4  848.26   676.4  882.94   702.6  898.69
#Mann= 8 ,-1,0
       0      .1       0     150     .07       0  277.12     .06       0
   309.8    .045       0   322.8     .06       0  383.01     .08       0
  483.01     .06       0  583.01      .1       0
#XS Ineff= 2 , 0
                          352.55          826.09
Permanent Ineff=
       F       F
Bank Sta=309.8,322.8
XS Rating Curve= 0 ,0
Exp/Cntr(USF)=0,0
Exp/Cntr=0.3,0.1

Type RM Length L Ch R = 1 ,401     ,326.8,326.8,326.8
XS GIS Cut Line= 5
1665141.66447016396923.062948465 1664945.6154468396795.505766339
1664866.25072812 396817.971713591664541.93538721396830.830127618
1664478.61862542396921.467523049
#Sta/Elev= 30
       0  933.81    41.3   917.6      56  909.44    69.4   900.8      83  893.67
    97.3  884.37     107  876.18   116.4  863.22   121.5  857.29   144.6  838.22
   167.7  834.81   179.3  826.69     188  823.22   193.8  821.96   310.3   820.1
   314.4  819.48   330.5  812.98   342.5   812.5   347.4812.9907   350.5  813.82
   358.5  818.47   362.5  818.99     416  818.25   555.8  819.33   630.8  820.72
   640.5  822.14   667.4  838.75   696.7  859.87   716.2  875.57   751.5  898.78
#Mann= 9 ,-1,0
       0      .1       0     120     .07       0  293.89     .06       0
   330.5    .045       0   347.4     .06       0  396.38     .08       0
  486.38     .06       0  680.95      .1       0  720.95     .06       0
Bank Sta=330.5,347.4
XS Rating Curve= 0 ,0
Exp/Cntr(USF)=0,0
Exp/Cntr=0.3,0.1

Type RM Length L Ch R = 1 ,74      ,,,
XS GIS Cut Line= 4
1665125.62239762396883.135728479 1664781.3854882396499.259417362
1664652.03586163396545.1576719521664435.06229447396870.618022681
#Sta/Elev= 30
       0   909.5    14.2  897.88    36.9  883.04    46.5  875.59    51.1   870.6
    62.6   854.3      68  849.94    73.3  848.03    89.5  846.73    94.8  843.16
   110.9  825.95   116.3  823.93   137.8  823.29   159.3  817.69   184.2  815.41
   539.5  812.36   553.6810.7198   559.4  810.42   564.6  810.72   576.4  813.23
   589.1  814.05   900.4  813.54   921.3  814.59   940.6  819.55   962.8  820.17
   966.8  821.79   984.1  833.05  1006.1  850.95  1022.3  865.61    1044  881.41
#Mann= 11 ,-1,0
       0      .1       0      30     .06       0      60     .07       0
     160     .05       0     210     .06       0     300     .05       0
     350      .1       0   553.6    .045       0   564.6      .1       0
  682.87     .05       0  922.87     .06       0
Bank Sta=553.6,564.6
XS Rating Curve= 0 ,0
Exp/Cntr(USF)=0,0
Exp/Cntr=0.3,0.1
LCMann Table=0

Chan Stop Cuts=-1
Use User Specified Reach Order=0
Composite Channel Slope=5